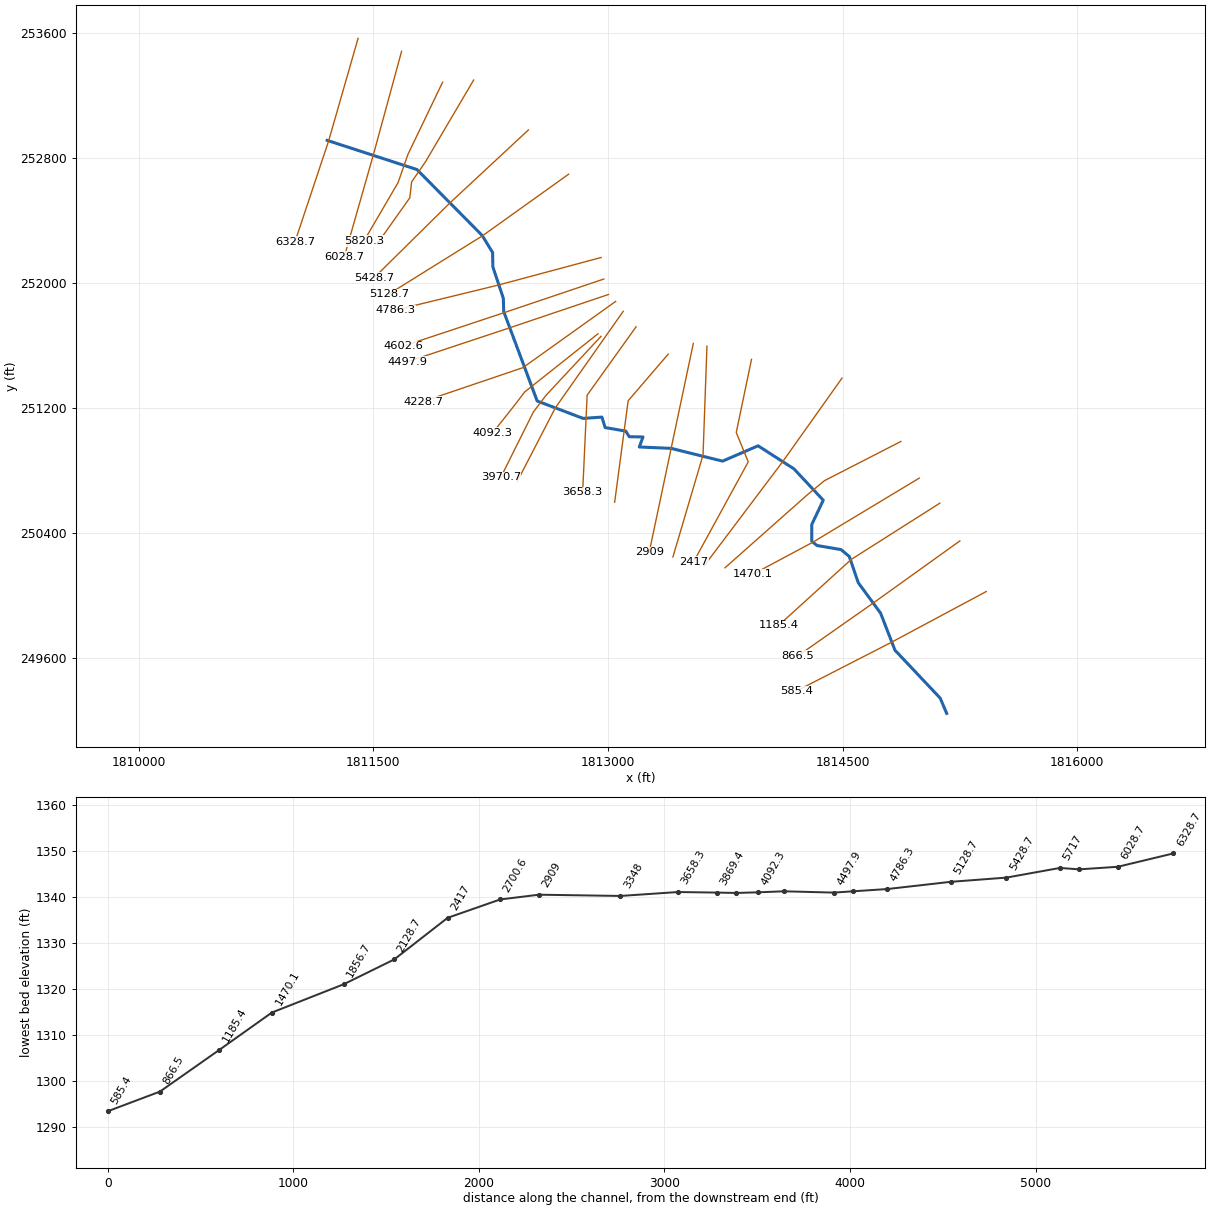
--- FOXGRAPERN.prj (project) ---

Proj Title=FOXGRAPERN
Current Plan=p01
Default Exp/Contr=0,0
English Units
Geom File=g01
Flow File=f01
Plan File=p01
BEGIN DESCRIPTION:
END DESCRIPTION:
DSS Export Rating Curves= 0
DSS Export Rating Curve Sorted= 0
DSS Export Volume Flow Curves= 0
DXF OffsetX= 0
DXF OffsetY= 0
DXF ScaleX= 0
DXF ScaleY= 0

--- FOXGRAPERN.p01 (plan) ---

Plan Title=Floodplain
Program Version=4.00
Geom File=g01
Flow File=f01
K Sum by GR=0
Std Step Tol=0.01
Critical Tol=0.01
Num of Std Step Trials=20
Max Error Tol=0.3
Flow Tol Ratio=0.001
Split Flow NTrial=30
Split Flow Tol=0.02
Split Flow Ratio=0.02
Log Output Level=0
Friction Slope Method=1
Unsteady Friction Slope Method=2
Unsteady Bridges Friction Slope Method=1
Global Log Level=0
CheckData=False
Run HTab=0
Run UNet=0
Run PostProcess=0
UNET Theta=0
UNET Theta Warmup=0
UNET ZTol=0
UNET ZSATol=0
UNET MxIter=0
UNET MaxInSteps=0
UNET DtIC=0
UNET DtMin=0
UNET MaxCRTS=0
UNET WFStab=0
UNET SFStab=0
UNET WFX=0
UNET SFX=0
UNET DSS MLevel=0
UNET DZMax Abort=0
UNET Convert EG Bridges=0
UNET Use Existing IB Tables=0
UNET Froude Limit=0
UNET Froude Power=0
Write IC File=0
Echo Input=False
Echo Output=False
Write Detailed=0

--- FOXGRAPERN.f01 (steady flow) ---

Flow Title=NFF Regression Equation
Program Version=4.00
Number of Profiles=1
Profile Names=P100yr
River Rch & RM=FOXGRAPERN,Main      ,6328.7
506.4061
River Rch & RM=FOXGRAPERN,Main      ,6028.7
586.1722
River Rch & RM=FOXGRAPERN,Main      ,5428.7
594.5965
River Rch & RM=FOXGRAPERN,Main      ,2909
658.2449
River Rch & RM=FOXGRAPERN,Main      ,585.4
729.8348
Boundary for River Rch & Prof#=FOXGRAPERN,Main      ,1
Up Type=0
Dn Type=3
Dn Slope=0.024055

--- FOXGRAPERN.g01 (geometry) ---

Geom Title=USGS 10m DEM
Program Version=4.10

River Reach=FOXGRAPERN      ,Main
Reach XY= 30
     1811204.338      252913.799       1811778.4      252726.741
     1812195.046      252304.973       1812262.2      252195.274
     1812263.451      252103.928     1812330.605      251902.048
     1812333.108      251816.542     1812547.084      251243.854
     1812840.727      251132.487     1812960.853      251140.829
     1812981.325       251073.75     1813113.561       251050.79
     1813135.204       251015.28      1813223.63      251013.611
     1813199.855      250949.377     1813403.761      250940.407
     1813732.293      250858.622     1813959.336      250956.946
     1814188.805      250809.065      1814376.02      250608.159
     1814302.629      250452.774      1814302.26      250345.694
      1814335.64      250318.194     1814489.375      250292.033
     1814542.547      250247.564     1814599.853      250079.735
     1814742.558      249884.811     1814834.608      249647.166
     1815123.835      249340.188     1815165.112      249242.603

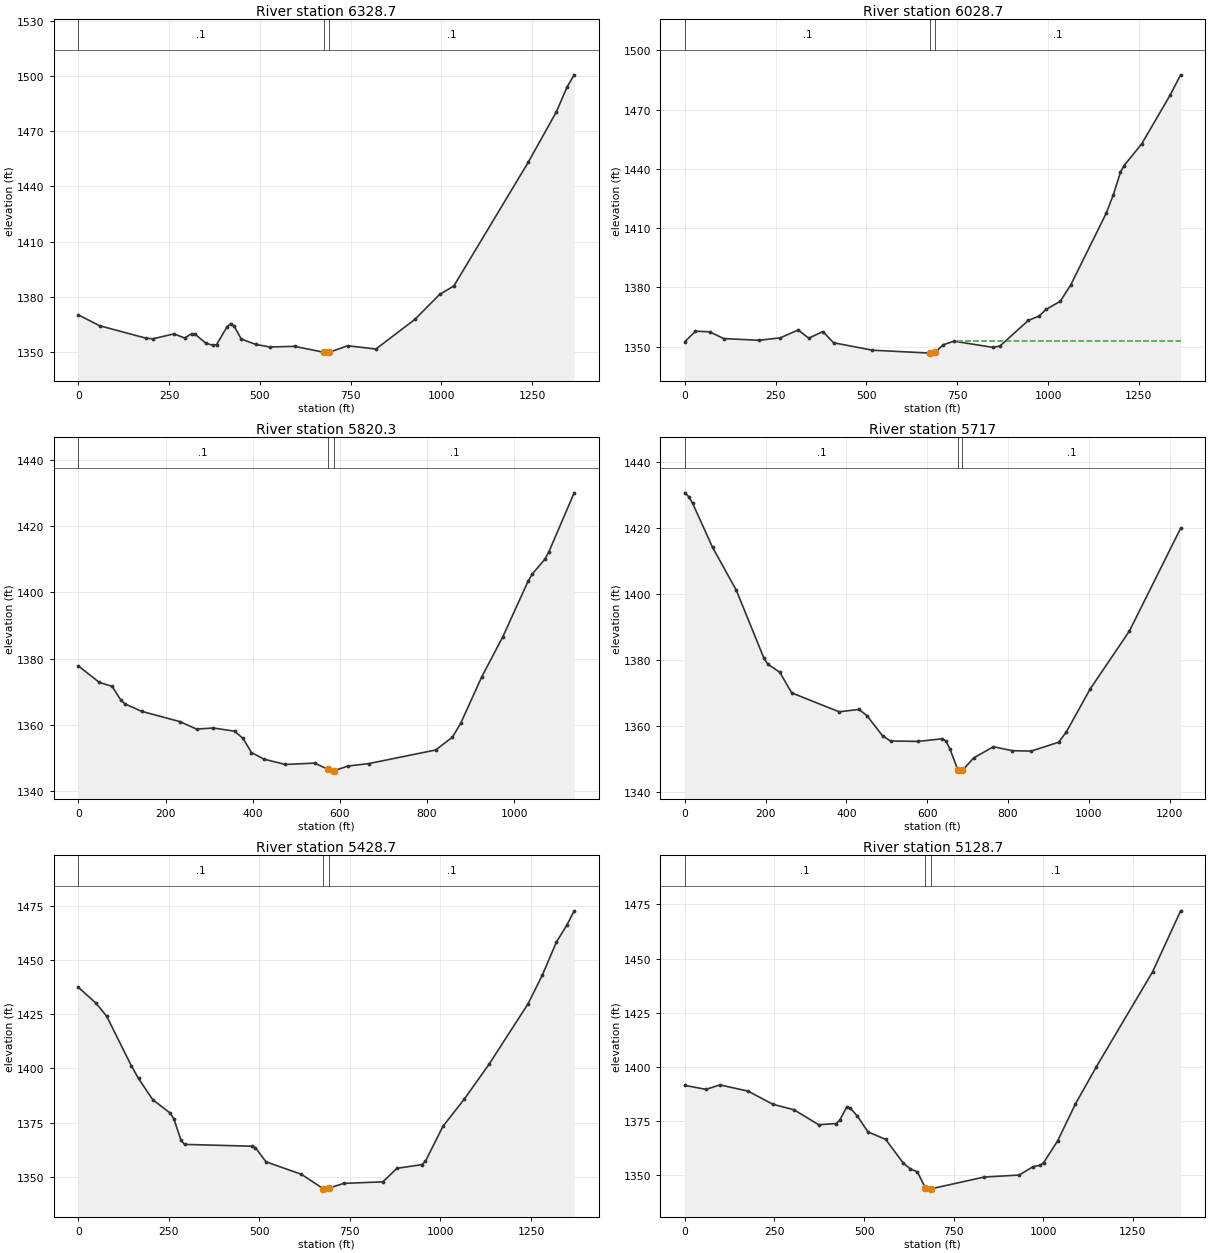
Type RM Length L Ch R = 1 ,6328.7  ,299.3,300,300.6
XS GIS Cut Line= 3
        1811402.      253567.457     1811213.827      252910.641
     1810998.367      252263.181
#Sta/Elev= 30
       0 1370.33    58.6 1364.44   185.4 1357.74     205 1357.33   263.5 1360.03
   292.8 1357.78   312.3 1360.09   322.1 1359.77   351.4 1354.94   370.9 1353.84
   380.7 1354.18   409.9 1363.98   419.7 1365.61   429.5 1364.09     449 1357.18
     488 1354.36   527.1 1352.91   595.4 1353.26   675.7 1350.07   683.2 1349.58
   690.7 1350.01   741.7 1353.58   819.7 1351.81   926.9 1367.88   995.2 1381.44
  1034.2 1386.02  1238.9 1453.06  1316.9 1480.58  1346.1 1493.98  1365.6 1500.56
#Mann= 3 , 0 , 0
       0      .1       0   675.7    .045       0   690.7      .1       0
#XS Ineff= 2 , 0
       0                   741.7       0 1353.58
Permanent Ineff=
       F       F
Bank Sta=675.7,690.7
XS Rating Curve= 0 ,0
Exp/Cntr=0.3,0.1

Type RM Length L Ch R = 1 ,6028.7  ,210,208.4,207.1
XS GIS Cut Line= 3
      1811680.29      253484.575     1811501.051      252826.041
     1811314.356      252169.517
#Sta/Elev= 30
       0  1352.4    29.2 1357.77    68.2 1357.48   107.2 1354.03   204.8 1353.18
   263.2 1354.42     312 1358.42   341.2 1354.25   380.2 1357.59   409.5 1351.93
   516.7 1348.15     675 1346.69   682.5 1346.67     690 1347.23   711.7 1350.93
     741 1352.71   848.2 1349.59   867.8 1350.29   945.8 1363.26     975  1365.4
   994.5 1368.79  1033.5  1372.9  1062.8 1381.33  1160.3 1417.58  1179.8 1426.88
  1199.3 1438.28    1209 1441.59  1257.8 1452.64  1335.8 1477.22    1365 1487.62
#Mann= 3 , 0 , 0
       0      .1       0     675    .045       0     690      .1       0
#XS Ineff= 2 , 0
       0                   750.8       0 1352.81
Permanent Ineff=
       F       F
Bank Sta=675,690
XS Rating Curve= 0 ,0
Exp/Cntr=0.3,0.1

Type RM Length L Ch R = 1 ,5820.3  ,109.2,103.3,97.3
XS GIS Cut Line= 4
     1811942.426      253286.464     1811720.638      252823.357
     1811657.707      252643.394     1811439.503      252268.946
#Sta/Elev= 30
       0 1377.84    48.4 1372.83    77.5 1371.68    96.9 1367.65   106.6  1366.4
   145.3 1364.14   232.5 1361.05   271.3 1358.79     310 1359.11   358.5 1358.15
   377.8 1355.97   397.2 1351.72   426.3  1349.7   474.7 1348.13   542.1 1348.52
   572.5 1346.69   580.2 1346.11   587.5 1346.27   618.3 1347.64     666 1348.38
   819.7 1352.48   858.2 1356.35   877.5 1360.63   925.6 1374.57   973.8  1386.6
  1031.6 1403.31  1041.2 1405.48  1070.1 1409.97  1079.7 1412.29  1137.5    1430
#Mann= 3 , 0 , 0
       0      .1       0   572.5    .045       0   587.5      .1       0
Bank Sta=572.5,587.5
XS Rating Curve= 0 ,0
Exp/Cntr=0.3,0.1

Type RM Length L Ch R = 1 ,5717    ,293,288.3,283.4
XS GIS Cut Line= 5
     1812140.823       253300.18     1811832.885       252776.59
     1811744.343      252647.684     1811732.531       252545.51
     1811524.288      252251.122
#Sta/Elev= 30
       0 1430.74     9.8 1429.59    19.6 1427.51    68.6 1414.25   127.4 1401.26
     196  1380.6   205.7 1378.81   235.1 1376.38   264.5 1370.13   382.1  1364.4
   431.1 1365.11   450.7 1363.27   489.9 1357.06   509.5 1355.55     578 1355.43
   636.8 1356.22   646.5 1355.54   656.3 1353.15   675.8 1346.81   685.6 1346.42
     687 1346.63     715  1350.4   763.8 1353.82   810.6 1352.61   857.3 1352.49
   925.2 1355.16   944.6 1358.32  1003.1 1371.25  1100.6 1388.89  1227.3    1420
#Mann= 3 , 0 , 0
       0      .1       0   675.8    .045       0     687      .1       0
Bank Sta=675.8,687
XS Rating Curve= 0 ,0
Exp/Cntr=0.3,0.1

Type RM Length L Ch R = 1 ,5428.7  ,302.6,300,294.7
XS GIS Cut Line= 3
     1812491.046      252980.552     1811990.208      252514.144
       1811503.4       252032.53
#Sta/Elev= 30
       0 1437.35    48.9 1430.03    78.2 1424.05   146.6 1401.11   166.2 1395.32
   205.3 1385.58   254.2  1379.3     264  1376.6   283.5 1366.88   293.3 1364.94
   479.1 1364.11   488.8 1363.48   518.2 1356.91   615.9 1351.16   676.9 1344.46
   684.4 1344.32   691.9 1344.79   733.3 1346.97   840.9 1347.68     880 1353.92
   948.5  1355.6   958.3 1357.11  1007.2 1373.36  1065.9 1385.83  1134.4 1401.94
    1242 1429.78  1281.1  1442.9  1320.2  1458.2  1349.6  1466.2  1369.2  1472.6
#Mann= 3 , 0 , 0
       0      .1       0   676.9    .045       0   691.9      .1       0
Bank Sta=676.9,691.9
XS Rating Curve= 0 ,0
Exp/Cntr=0.3,0.1

Type RM Length L Ch R = 1 ,5128.7  ,349.6,342.4,335.3
XS GIS Cut Line= 3
     1812748.164      252697.143     1812196.845      252302.074
     1811598.536      251928.868
#Sta/Elev= 30
       0 1391.37      59 1389.52    98.3 1391.58   176.9 1388.68   245.8 1382.61
   304.7 1380.08   373.5 1373.18   422.7 1373.72   432.5 1375.36   452.2 1381.49
     462 1380.78   481.7 1377.12   511.2 1369.83   560.3 1366.42   609.4 1355.48
   629.1 1352.77   648.8  1351.4   670.8 1344.12   678.3  1343.4   685.8 1343.51
     835 1348.98   932.9 1349.91   972.1 1353.84   991.7  1354.4  1001.5  1355.7
  1040.6 1365.84  1089.6 1382.68  1148.4 1399.99  1305.1 1443.82  1383.4 1472.04
#Mann= 3 , 0 , 0
       0      .1       0   670.8    .045       0   685.8      .1       0
Bank Sta=670.8,685.8
XS Rating Curve= 0 ,0
Exp/Cntr=0.3,0.1

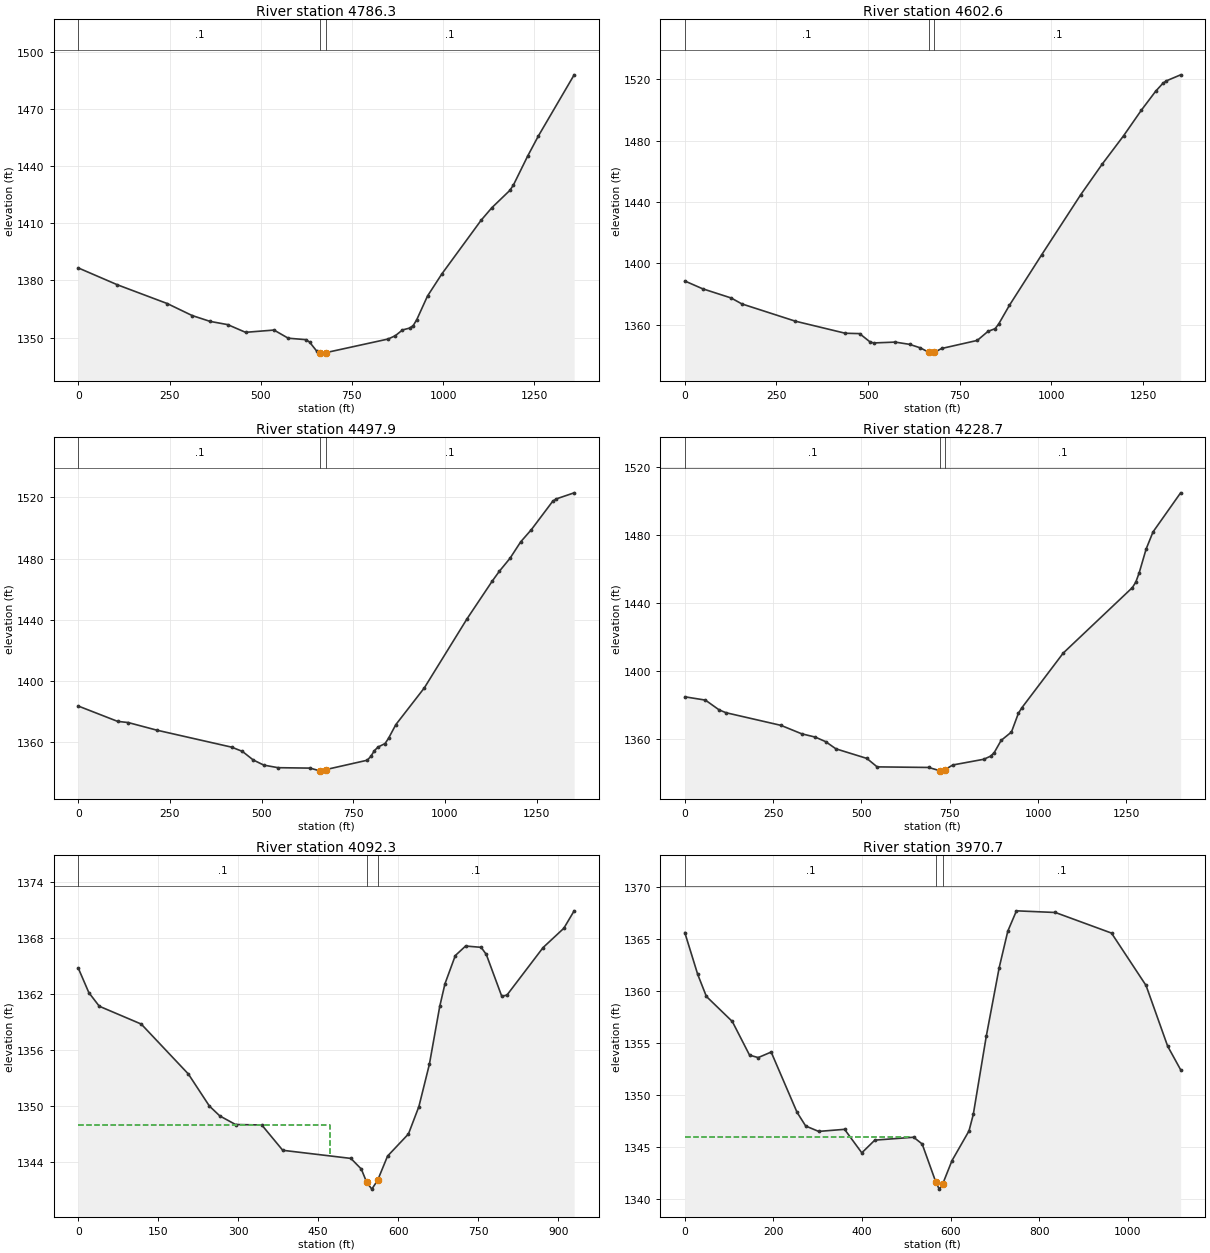
Type RM Length L Ch R = 1 ,4786.3  ,182,183.7,185.2
XS GIS Cut Line= 3
     1812956.081      252163.343     1812296.739      251986.287
     1811639.531       251825.81
#Sta/Elev= 30
       0 1386.54   107.3 1377.68   243.8 1367.85   312.1 1361.55   360.9  1358.5
   409.6 1356.78   458.4 1352.75   536.4 1353.94   575.4 1349.66   624.2 1348.89
   633.9 1347.62   653.4 1342.92   663.2 1341.83   663.7 1341.83   678.7 1342.09
   849.4 1349.24     869 1350.98   888.6 1353.99   908.2 1354.98     918 1356.28
   927.8 1359.42   957.2  1371.8   996.4 1383.37  1104.3 1411.61  1133.7 1418.18
  1182.7 1427.21  1192.5 1429.98  1231.8 1445.28  1261.2 1455.84  1359.2  1487.9
#Mann= 3 , 0 , 0
       0      .1       0   663.7    .045       0   678.7      .1       0
Bank Sta=663.7,678.7
XS Rating Curve= 0 ,0
Exp/Cntr=0.3,0.1

Type RM Length L Ch R = 1 ,4602.6  ,104.3,104.7,104.4
XS GIS Cut Line= 3
     1812973.095      252025.324      1812318.62      251804.237
     1811690.701      251595.423
#Sta/Elev= 30
       0 1388.39    48.6 1383.31   126.5  1377.3   155.7 1373.43   301.6 1362.17
   437.8  1354.3   476.8 1354.07   505.9 1348.53   515.7 1347.99     574 1348.53
     613 1347.07   642.2  1344.8   665.8 1341.86   671.4 1341.34   680.8 1341.82
   700.5 1344.36   797.8 1349.63     827 1355.52   846.5 1357.29   856.2 1360.34
   885.4 1372.49     973 1405.29  1080.1 1444.69  1138.4 1464.54  1196.8 1483.06
  1245.5 1499.81  1284.4 1512.13  1303.9 1517.24  1313.6  1518.9  1352.5 1522.83
#Mann= 3 , 0 , 0
       0      .1       0   665.8    .045       0   680.8      .1       0
Bank Sta=665.8,680.8
XS Rating Curve= 0 ,0
Exp/Cntr=0.3,0.1

Type RM Length L Ch R = 1 ,4497.9  ,261.9,269.2,269.2
XS GIS Cut Line= 3
     1813003.043      251926.365     1812348.568      251705.279
     1811720.649      251496.465
#Sta/Elev= 30
       0  1383.6     107  1373.6   136.2 1372.81     214 1367.85   418.4 1356.72
   447.6 1353.95   476.8  1348.4   505.9 1344.99   544.9 1343.31   632.4 1343.03
   659.8 1341.15   661.6 1341.06   674.8 1342.05   788.1 1348.19   797.8 1350.71
   807.6 1354.42   817.3 1356.77   836.8 1359.12   846.5 1362.67     866 1371.44
   943.8 1395.48  1060.6 1440.77  1128.7 1465.18  1148.2 1471.67  1177.4 1480.17
  1206.6 1490.94  1235.8 1498.95  1294.2 1517.56  1303.9 1519.06  1352.5 1523.01
#Mann= 3 , 0 , 0
       0      .1       0   659.8    .045       0   674.8      .1       0
Bank Sta=659.8,674.8
XS Rating Curve= 0 ,0
Exp/Cntr=0.3,0.1

Type RM Length L Ch R = 1 ,4228.7  ,135.4,136.4,144.1
XS GIS Cut Line= 3
     1813048.758      251881.873     1812455.826      251457.454
     1811817.378      251240.624
#Sta/Elev= 30
       0 1385.03    58.3 1383.09    97.2 1377.33   116.7 1375.67   272.2 1368.24
   330.6  1363.3   369.4 1361.33   398.6 1358.67   427.8 1354.44   515.3 1348.81
   544.4 1343.84   690.3  1343.5   721.7 1341.59   729.2 1341.34   736.7 1342.23
   758.5 1344.95   846.4 1348.32     866 1350.19   875.8 1352.23   895.3 1359.38
   924.6 1364.33   944.2 1375.33   953.9 1378.55  1071.2 1410.75  1266.6 1449.17
  1276.4 1452.38  1286.2 1457.95  1305.7 1471.86  1325.3 1481.95  1403.4 1504.92
#Mann= 3 , 0 , 0
       0      .1       0   721.7    .045       0   736.7      .1       0
Bank Sta=721.7,736.7
XS Rating Curve= 0 ,0
Exp/Cntr=0.3,0.1

Type RM Length L Ch R = 1 ,4092.3  ,116.2,121.6,127.1
XS GIS Cut Line= 4
     1812935.855      251674.634      1812466.53      251301.355
     1812413.578      251231.043     1812263.405      251040.939
#Sta/Elev= 30
       0 1364.78    19.7 1362.17    39.3 1360.71     118  1358.8   206.4 1353.45
   245.8 1350.02   265.4 1348.96   294.9 1348.04   344.1 1347.99   383.4 1345.28
   511.2 1344.41   530.8 1343.27   540.7 1341.87   550.5 1341.12   561.5 1342.08
     580 1344.66   619.2 1347.03   638.8 1349.97   658.4 1354.48   677.9  1360.7
   687.7 1363.12   707.1 1366.14   726.4 1367.16   755.5 1367.02   765.2 1366.26
   794.3 1361.76     804 1361.91   871.8    1367   910.6 1369.06     930 1370.93
#Mann= 3 , 0 , 0
       0      .1       0   540.7    .045       0   561.5      .1       0
#XS Ineff= 2 , 0
       0   471.9    1348               0
Permanent Ineff=
       F       F
Bank Sta=540.7,561.5
XS Rating Curve= 0 ,0
Exp/Cntr=0.3,0.1

Type RM Length L Ch R = 1 ,3970.7  ,99.8,101.3,105
XS GIS Cut Line= 4
     1812955.386      251658.357     1812603.443      251280.381
     1812522.432      251172.883     1812313.957         250754.
#Sta/Elev= 30
       0 1365.65    29.2 1361.62    48.7 1359.51   107.2  1357.1   146.2 1353.86
   165.7 1353.63   194.9 1354.16   253.4 1348.36   272.8 1347.05   302.1 1346.53
   360.6 1346.73   399.5 1344.47   428.8 1345.69   516.5 1345.97   535.7 1345.32
   566.6 1341.65   574.2 1340.98   581.6 1341.43     603 1343.72   641.4 1346.58
   651.1 1348.17   680.3 1355.66   709.6 1362.29     729 1365.79   748.5 1367.74
   836.3 1367.58     963  1365.6    1041 1360.56  1089.7 1354.73    1119 1352.46
#Mann= 3 , 0 , 0
       0      .1       0   566.6    .045       0   581.6      .1       0
#XS Ineff= 2 , 0
       0   506.7 1346.02               0
Permanent Ineff=
       F       F
Bank Sta=566.6,581.6
XS Rating Curve= 0 ,0
Exp/Cntr=0.3,0.1

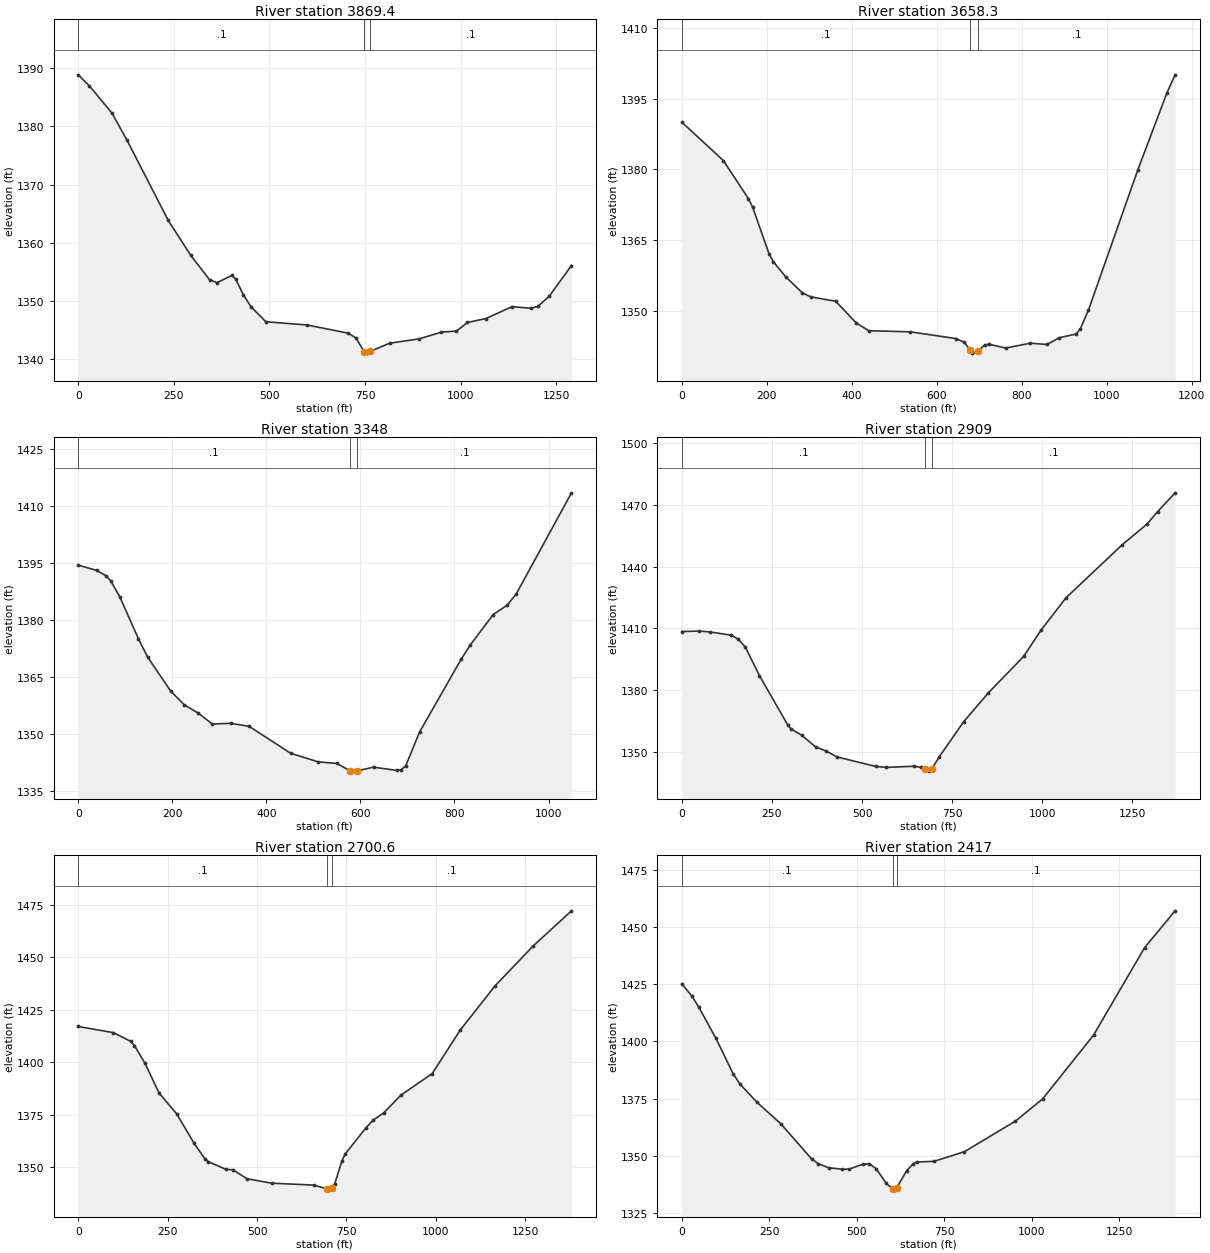
Type RM Length L Ch R = 1 ,3869.4  ,197.9,211.1,220.9
XS GIS Cut Line= 3
     1813097.299      251818.628     1812663.039      251200.058
     1812418.124      250725.354
#Sta/Elev= 30
       0 1388.83    29.4 1386.92    88.3 1382.26   127.6 1377.61   235.6 1363.83
   294.5 1357.82   343.5 1353.67   363.2 1353.16   402.4 1354.42   412.2 1353.73
   431.9 1351.08   451.5 1349.06   490.8 1346.45   598.7 1345.89   706.7 1344.48
   726.3 1343.66   748.3 1341.27   755.8 1341.06   763.3 1341.35   814.1 1342.76
   891.8 1343.51     950 1344.67   988.9 1344.84    1018 1346.32  1066.6    1347
  1134.6 1349.04  1183.1 1348.76  1202.5 1349.09  1231.7 1350.82    1290  1356.1
#Mann= 3 , 0 , 0
       0      .1       0   748.3    .045       0   763.3      .1       0
Bank Sta=748.3,763.3
XS Rating Curve= 0 ,0
Exp/Cntr=0.3,0.1

Type RM Length L Ch R = 1 ,3658.3  ,306.3,310.3,308
XS GIS Cut Line= 3
     1813179.242      251719.176     1812866.471      251281.386
     1812837.648      250659.078
#Sta/Elev= 30
       0    1390    97.8 1381.87   156.5 1373.86   166.3 1372.12   205.4 1362.12
   215.2 1360.52   244.6 1357.29   283.7 1353.92   303.3 1353.08     362 1352.14
   410.9 1347.52   440.2 1345.92     538 1345.68   645.1 1344.26   664.6 1343.51
   678.2 1341.86     684 1341.18  695.95 1341.57   713.2 1342.93     723 1343.06
   761.9 1342.25   820.3 1343.28   859.3 1343.01   888.5 1344.44   927.4 1345.21
   937.1 1346.18   956.6  1350.2  1073.4 1379.97  1141.6  1396.2    1161 1400.01
#Mann= 3 , 0 , 0
       0      .1       0   678.2    .045       0  695.95      .1       0
Bank Sta=678.2,695.95
XS Rating Curve= 0 ,0
Exp/Cntr=0.3,0.1

Type RM Length L Ch R = 1 ,3348    ,380.5,438.9,431.6
XS GIS Cut Line= 3
     1813384.407      251543.823     1813128.671      251245.271
     1813042.361      250595.297
#Sta/Elev= 30
       0 1394.53    39.3 1393.13      59 1391.74    68.8 1390.46    88.4  1386.2
   127.8 1375.22   147.4 1370.38   196.6  1361.4     226 1357.72   255.5 1355.59
     285 1352.72   324.3 1352.91   363.6 1352.11   451.8 1345.02   510.5 1342.76
   549.7 1342.36   578.2 1340.41   588.8 1340.33   593.2 1340.42     628 1341.37
   676.9 1340.53   686.7 1340.69   696.5 1341.75   725.8 1350.61   813.9 1369.71
   833.5  1373.5   882.4 1381.53   911.8 1383.96   931.4 1386.96  1048.8 1413.55
#Mann= 3 , 0 , 0
       0      .1       0   578.2    .045       0   593.2      .1       0
Bank Sta=578.2,593.2
XS Rating Curve= 0 ,0
Exp/Cntr=0.3,0.1

Type RM Length L Ch R = 1 ,2909    ,205.2,208.5,206.5
XS GIS Cut Line= 2
     1813545.188      251612.524     1813262.969      250273.377
#Sta/Elev= 30
       0 1408.51    48.9 1408.74    78.2 1408.31   136.9 1406.72   156.4 1404.81
     176 1400.99   215.1 1387.12   293.3  1363.2     303 1361.12   332.4 1358.05
   371.5 1352.35   400.8 1350.34   430.1 1347.53   537.6 1342.89     567 1342.42
   645.2 1342.99   664.7 1342.38   674.5 1341.49   684.3  1340.6   694.3 1341.86
   713.6 1347.45     782 1364.67   850.5  1378.7   948.2 1396.39   997.1 1409.34
  1065.5 1424.88  1221.9 1450.76  1290.4 1460.77  1319.7 1466.81  1368.6 1475.99
#Mann= 3 , 0 , 0
       0      .1       0   674.5    .045       0   694.3      .1       0
Bank Sta=674.5,694.3
XS Rating Curve= 0 ,0
Exp/Cntr=0.3,0.1

Type RM Length L Ch R = 1 ,2700.6  ,273.4,283.6,298.8
XS GIS Cut Line= 3
     1813632.489      251595.376     1813607.452      250898.086
     1813414.887      250244.564
#Sta/Elev= 30
       0 1417.07    98.3 1414.15   147.4 1409.94   157.2 1408.01   186.7 1399.52
     226  1385.4   275.2 1375.46   324.3 1361.34   353.8 1354.11   363.6  1352.7
   412.8 1348.98   432.4 1348.79   471.7 1344.52   540.5 1342.41   658.4  1341.5
   694.4 1339.73   697.7 1339.57   709.4 1340.29   717.2 1342.09   736.7 1352.79
   746.4 1356.32   804.8 1368.88   824.3  1372.4   853.5 1375.83   902.1 1384.35
   989.7 1394.63  1067.6 1415.26  1164.9 1436.36    1272 1455.46    1379 1472.19
#Mann= 3 , 0 , 0
       0      .1       0   694.4    .045       0   709.4      .1       0
Bank Sta=694.4,709.4
XS Rating Curve= 0 ,0
Exp/Cntr=0.3,0.1

Type RM Length L Ch R = 1 ,2417    ,310.6,288.2,264.3
XS GIS Cut Line= 4
     1813917.361      251510.661     1813819.882      251042.466
     1813896.386       250853.95     1813547.436      250214.091
#Sta/Elev= 30
       0 1425.12    29.3 1419.66    48.8 1414.87    97.6 1401.31   146.4 1385.98
   165.9 1381.45   214.7 1373.47     283 1364.07   370.9 1348.79   390.4 1346.65
   419.7  1344.9   458.7 1344.25   478.2  1344.3     517 1346.41   536.4 1346.59
   555.7 1344.45   584.8 1338.03   602.5 1335.72   604.2 1335.57   613.9 1336.03
   642.9 1343.65   662.3  1346.7     672 1347.41   720.6 1347.68     808  1351.9
   953.8 1365.25  1031.5 1374.92  1177.3  1402.8    1323  1440.9  1410.5 1456.99
#Mann= 3 , 0 , 0
       0      .1       0   602.5    .045       0   613.9      .1       0
Bank Sta=602.5,613.9
XS Rating Curve= 0 ,0
Exp/Cntr=0.3,0.1

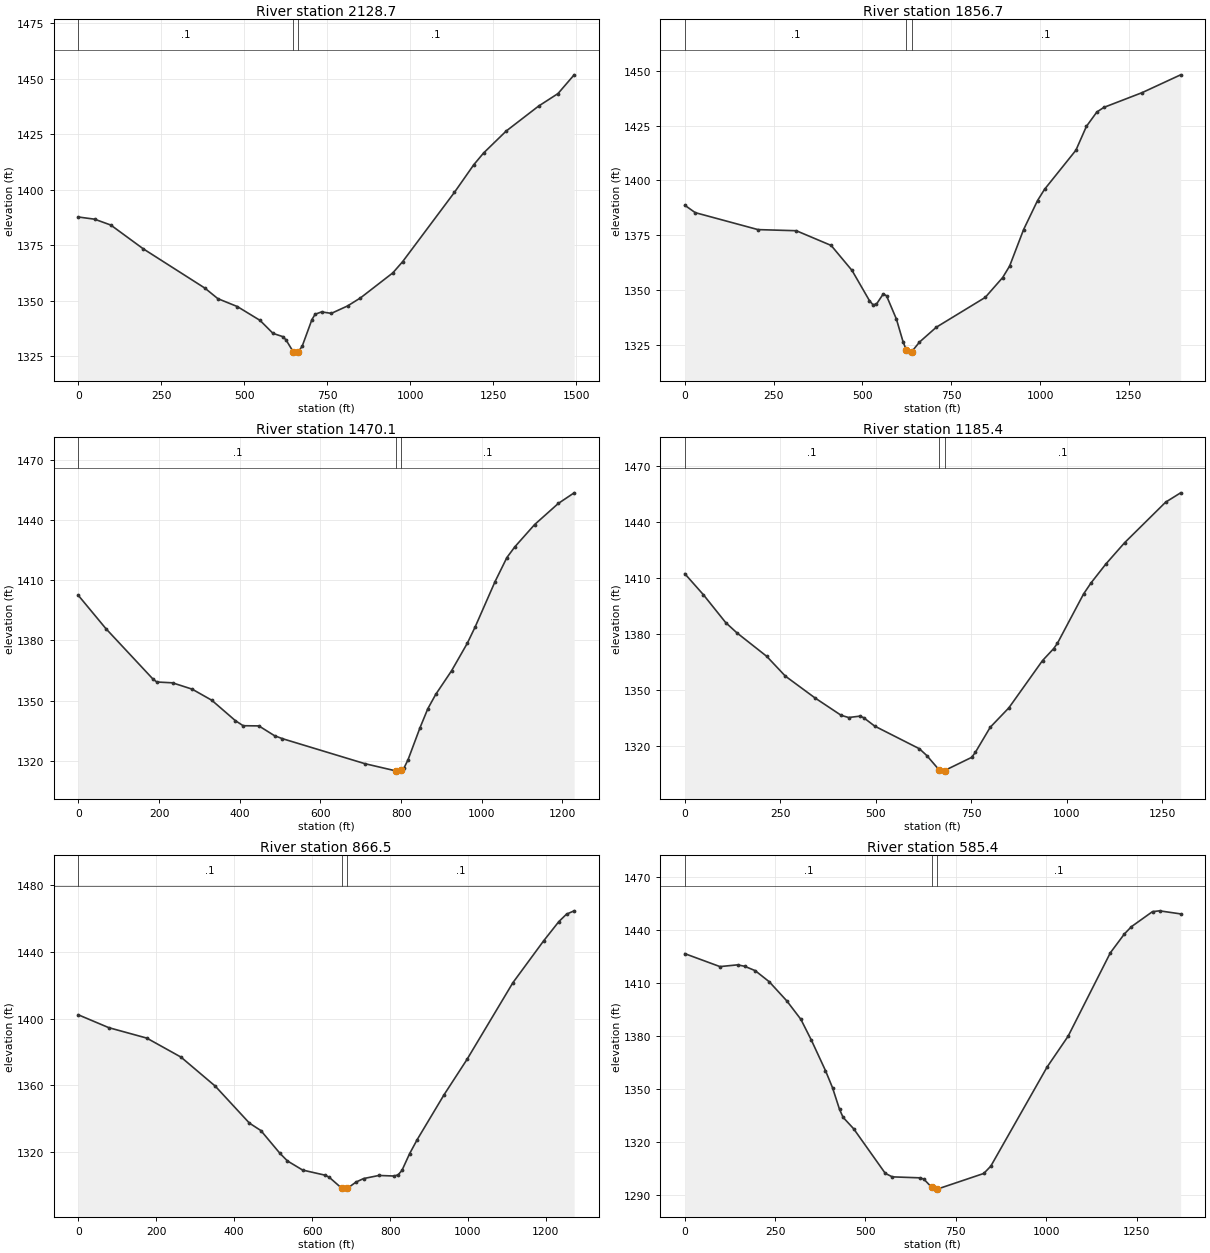
Type RM Length L Ch R = 1 ,2128.7  ,277.5,272,266.1
XS GIS Cut Line= 3
        1814496.      251390.541     1814117.306      250856.217
     1813613.162      250185.789
#Sta/Elev= 30
       0 1387.74    48.9 1386.76    97.8 1384.12   195.5 1373.44   381.2 1355.76
   420.3 1351.01     479 1347.46   547.4 1341.24   586.5 1335.39   615.8 1333.94
   625.6 1332.48   647.4 1327.11   654.9 1326.51   662.4 1327.05   674.4 1329.63
   703.7  1341.6   713.4    1344   732.9 1345.06   762.2 1344.39     811 1347.73
     850 1351.35   947.5 1362.62   976.8 1367.62  1132.8 1398.78  1191.4 1411.27
  1220.6 1416.49  1288.9  1426.4  1386.4 1437.61    1445 1443.26  1493.7 1451.69
#Mann= 3 , 0 , 0
       0      .1       0   647.4    .045       0   662.4      .1       0
Bank Sta=647.4,662.4
XS Rating Curve= 0 ,0
Exp/Cntr=0.3,0.1

Type RM Length L Ch R = 1 ,1856.7  ,390.2,386.6,381.2
XS GIS Cut Line= 4
      1814872.21      250984.617     1814383.738      250733.513
     1814276.407       250644.93     1813747.751      250175.221
#Sta/Elev= 30
       0 1388.68    29.4  1385.3     206 1377.55   313.8 1377.04   411.9 1370.32
   470.8 1358.87   519.8 1345.08   529.6 1343.23   539.4 1343.49   558.5 1348.14
   567.8 1347.33   595.6 1336.68   614.2  1326.4   623.7 1322.44   632.7 1321.12
   638.7 1321.77   660.6 1326.17     708 1332.96   845.6 1346.57   894.7 1355.65
   914.3 1360.91   953.6 1377.56   992.9 1390.84  1012.5 1395.94  1100.9 1413.83
  1130.4 1424.71  1159.8 1431.27  1179.5 1433.38  1287.5 1440.14  1395.6 1448.26
#Mann= 3 , 0 , 0
       0      .1       0   623.7    .045       0   638.7      .1       0
Bank Sta=623.7,638.7
XS Rating Curve= 0 ,0
Exp/Cntr=0.3,0.1

Type RM Length L Ch R = 1 ,1470.1  ,283.9,284.7,290.3
XS GIS Cut Line= 3
     1814990.127      250750.082      1814307.33      250337.913
     1813927.001      250134.391
#Sta/Elev= 30
       0 1402.41    68.1 1385.92   184.8 1360.82   194.5 1359.32   233.4 1358.91
   282.1 1355.76   330.7 1350.25     389 1340.13   408.5 1337.57   447.4 1337.48
   486.3  1332.6   505.8 1331.13     710  1318.7   787.8 1315.06   797.6 1314.98
  799.97 1315.47   807.4 1316.64   817.2 1320.65   846.6 1336.45   866.2 1346.03
   885.8 1353.16     925 1364.88   964.2 1378.64   983.8 1386.84  1032.8 1409.25
  1062.2 1421.24  1081.9 1426.57  1130.9 1437.64  1189.7 1448.16  1228.9 1453.43
#Mann= 3 , 0 , 0
       0      .1       0   787.8    .045       0  799.97      .1       0
Bank Sta=787.8,799.97
XS Rating Curve= 0 ,0
Exp/Cntr=0.3,0.1

Type RM Length L Ch R = 1 ,1185.4  ,317.7,318.9,315.9
XS GIS Cut Line= 3
     1815121.879      250589.653     1814554.577       250228.66
     1814092.205      249807.677
#Sta/Elev= 30
       0 1412.34    48.7  1401.1   107.2 1386.18   136.4 1380.73   214.4 1368.18
   263.1 1357.62   341.1  1345.9   409.3 1336.64   428.8 1335.48     458  1336.2
   467.8 1335.43     497 1330.89     614 1318.78   633.4 1315.14   664.9 1307.66
   672.4 1306.82   679.9 1307.13   750.6 1314.16   760.4 1316.84   799.4 1330.27
   848.3 1340.68   936.2  1365.9   965.5 1372.32   975.3 1375.17  1043.7 1401.51
  1063.2 1407.42  1102.3 1417.59  1151.2 1428.93  1258.6  1450.6  1297.7 1455.57
#Mann= 3 , 0 , 0
       0      .1       0   664.9    .045       0   679.9      .1       0
Bank Sta=664.9,679.9
XS Rating Curve= 0 ,0
Exp/Cntr=0.3,0.1

Type RM Length L Ch R = 1 ,866.5   ,284.1,281.1,277.9
XS GIS Cut Line= 3
      1815249.55      250347.604      1814694.84      249949.072
     1814212.648      249610.194
#Sta/Elev= 30
       0 1402.33    78.1 1394.63   175.6 1388.37   263.4 1376.97   351.3 1359.57
   439.1 1337.36   468.4 1332.92   517.2 1319.29   536.7 1314.67   575.7 1309.21
   634.2 1306.09     644 1304.86   675.5 1298.42     683 1297.78   690.5 1298.26
   712.5    1302   732.1 1304.12   771.4 1305.98   810.7 1305.64   820.6 1306.37
   830.4 1308.96     850 1318.99   869.7 1327.52   938.4 1354.34   997.4 1375.58
  1115.2  1421.6  1193.8 1446.61  1233.1 1458.24  1252.8  1462.7  1272.4  1464.7
#Mann= 3 , 0 , 0
       0      .1       0   675.5    .045       0   690.5      .1       0
Bank Sta=675.5,690.5
XS Rating Curve= 0 ,0
Exp/Cntr=0.3,0.1

Type RM Length L Ch R = 1 ,585.4   ,585.9,585.4,584
XS GIS Cut Line= 3
     1815418.177      250023.227     1814809.201      249696.614
     1814203.487      249385.386
#Sta/Elev= 30
       0 1426.64    97.3 1419.32     146 1420.31   165.5 1419.51   194.7 1417.04
   233.6 1410.77   282.2 1399.95   321.2  1389.5   350.4 1377.67   389.3 1360.52
   408.8 1350.82   428.2 1338.58     438  1334.1   467.2 1327.65   554.8 1302.42
   574.2 1300.45   652.1 1299.88   661.8 1299.09   683.5 1294.49   698.5 1293.51
   827.2 1302.36   846.7 1306.49  1002.4  1362.5  1060.7 1379.97  1177.5 1427.11
  1216.4 1437.78  1235.8 1441.89  1294.2  1450.4  1313.7 1450.85    1372 1449.11
#Mann= 3 , 0 , 0
       0      .1       0   683.5    .045       0   698.5      .1       0
Bank Sta=683.5,698.5
XS Rating Curve= 0 ,0
Exp/Cntr=0.3,0.1

Chan Stop Cuts=-1
Use User Specified Reach Order=0
Composite Channel Slope=5